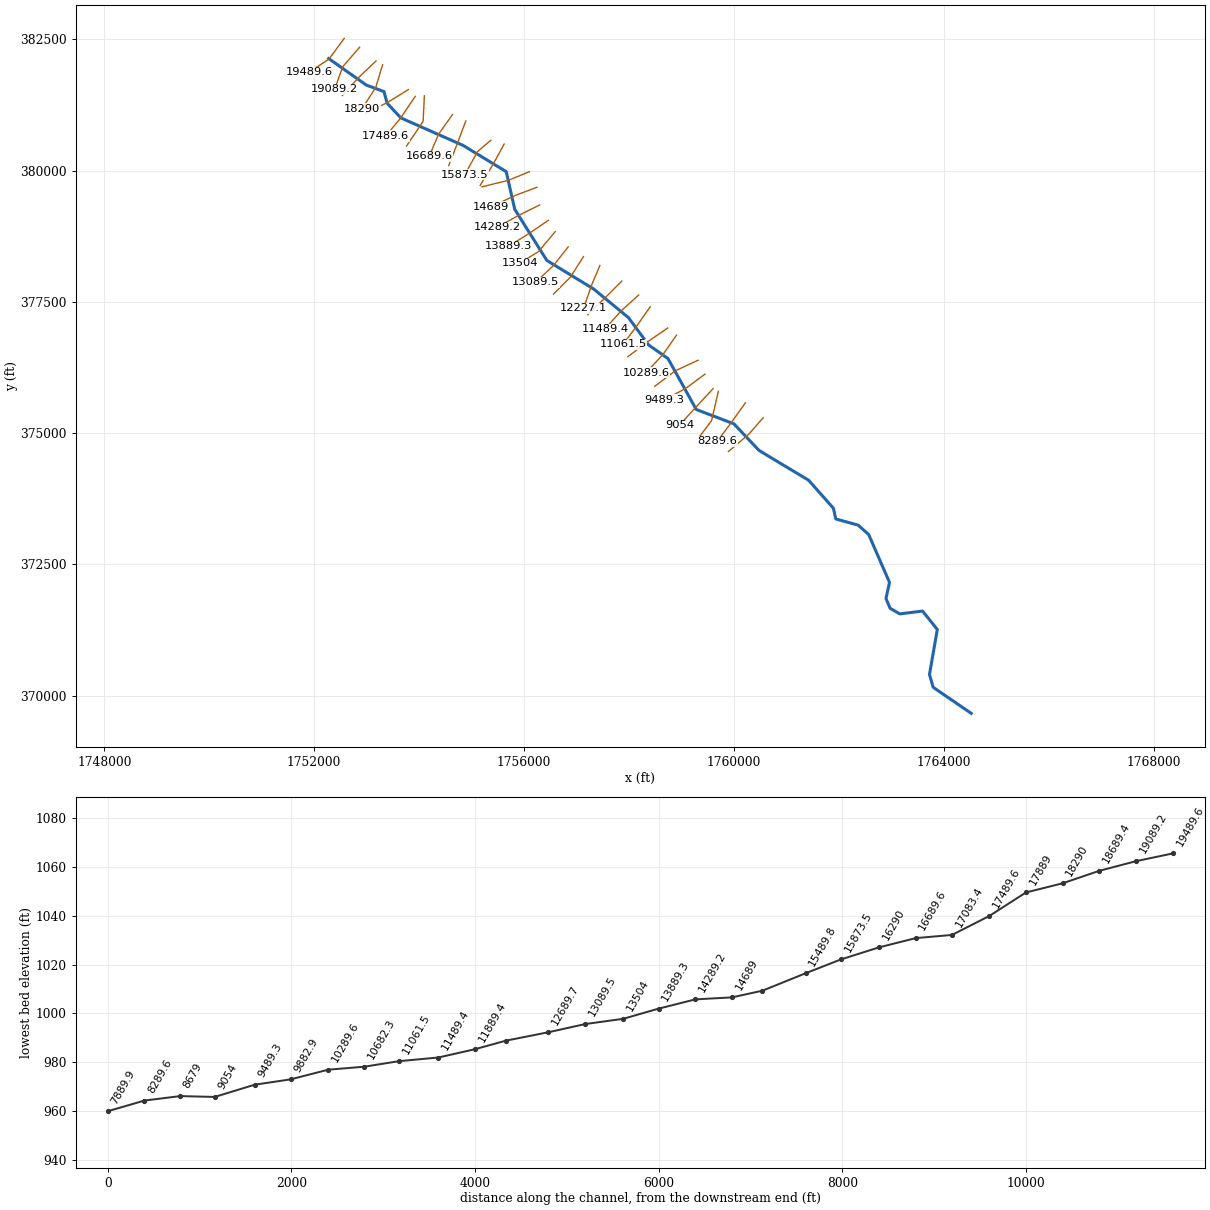
--- DrnkrdMlRn.prj (project) ---

Proj Title=DrnkrdMlRn
Current Plan=p01
Default Exp/Contr=0,0
English Units
Geom File=g01
Flow File=f01
Plan File=p01
BEGIN DESCRIPTION:
END DESCRIPTION:
DSS Export Rating Curves= 0
DSS Export Rating Curve Sorted= 0
DSS Export Volume Flow Curves= 0
DXF OffsetX= 0
DXF OffsetY= 0
DXF ScaleX= 0
DXF ScaleY= 0

--- DrnkrdMlRn.p01 (plan) ---

Plan Title=Floodplain
Program Version=4.00
Geom File=g01
Flow File=f01
K Sum by GR=0
Std Step Tol=0.01
Critical Tol=0.01
Num of Std Step Trials=20
Max Error Tol=0.3
Flow Tol Ratio=0.001
Split Flow NTrial=30
Split Flow Tol=0.02
Split Flow Ratio=0.02
Log Output Level=0
Friction Slope Method=1
Unsteady Friction Slope Method=2
Unsteady Bridges Friction Slope Method=1
Global Log Level=0
CheckData=False
Run HTab=0
Run UNet=0
Run PostProcess=0
UNET Theta=0
UNET Theta Warmup=0
UNET ZTol=0
UNET ZSATol=0
UNET MxIter=0
UNET MaxInSteps=0
UNET DtIC=0
UNET DtMin=0
UNET MaxCRTS=0
UNET WFStab=0
UNET SFStab=0
UNET WFX=0
UNET SFX=0
UNET DSS MLevel=0
UNET DZMax Abort=0
UNET Convert EG Bridges=0
UNET Use Existing IB Tables=0
UNET Froude Limit=0
UNET Froude Power=0
Write IC File=0
Echo Input=False
Echo Output=False
Write Detailed=0

--- DrnkrdMlRn.f01 (steady flow) ---

Flow Title=NFF Regression Equation
Program Version=4.00
Number of Profiles=1
Profile Names=P100yr
River Rch & RM=DrnkrdMlRn,Main      ,19489.6
755.7722
River Rch & RM=DrnkrdMlRn,Main      ,17083.4
828.2421
River Rch & RM=DrnkrdMlRn,Main      ,16689.6
885.4690
River Rch & RM=DrnkrdMlRn,Main      ,15020.3
922.2518
River Rch & RM=DrnkrdMlRn,Main      ,15020.3
1498.817
River Rch & RM=DrnkrdMlRn,Main      ,11489.4
1627.820
River Rch & RM=DrnkrdMlRn,Main      ,4618.1
1808.064
River Rch & RM=DrnkrdMlRn,Main      ,4289.1
2785.771
River Rch & RM=DrnkrdMlRn,Main      ,298
2905.030
Boundary for River Rch & Prof#=DrnkrdMlRn,Main      ,1
Up Type=0
Dn Type=3
Dn Slope=0.006033

--- DrnkrdMlRn.g01 (geometry) ---

Geom Title=USGS 3m DEM
Program Version=4.00

River Reach=DrnkrdMlRn      ,Main
Reach XY= 30
     1752275.882      382135.553     1752994.198      381629.911
     1753330.569      381506.213     1753389.163      381284.859
      1753651.75      381004.911     1754836.646      380481.907
     1755659.936      379981.315     1755821.889      379264.459
     1756433.868      378290.067     1757327.965      377745.362
     1757989.858      377200.657     1758371.802      376681.994
     1758742.896      376421.577      1759281.09      375451.525
     1759999.406      375178.088     1760476.837      374672.445
     1761423.017      374103.869     1761896.108      373570.015
      1761941.68      373366.022     1762367.028      373248.834
     1762568.851      373068.713      1762965.25      372156.698
     1762897.556      371851.267     1762976.675       371664.51
     1763161.202      371557.988     1763594.336      371612.049
     1763875.976      371262.579     1763727.046      370402.911
     1763797.825      370159.609     1764523.136      369663.176

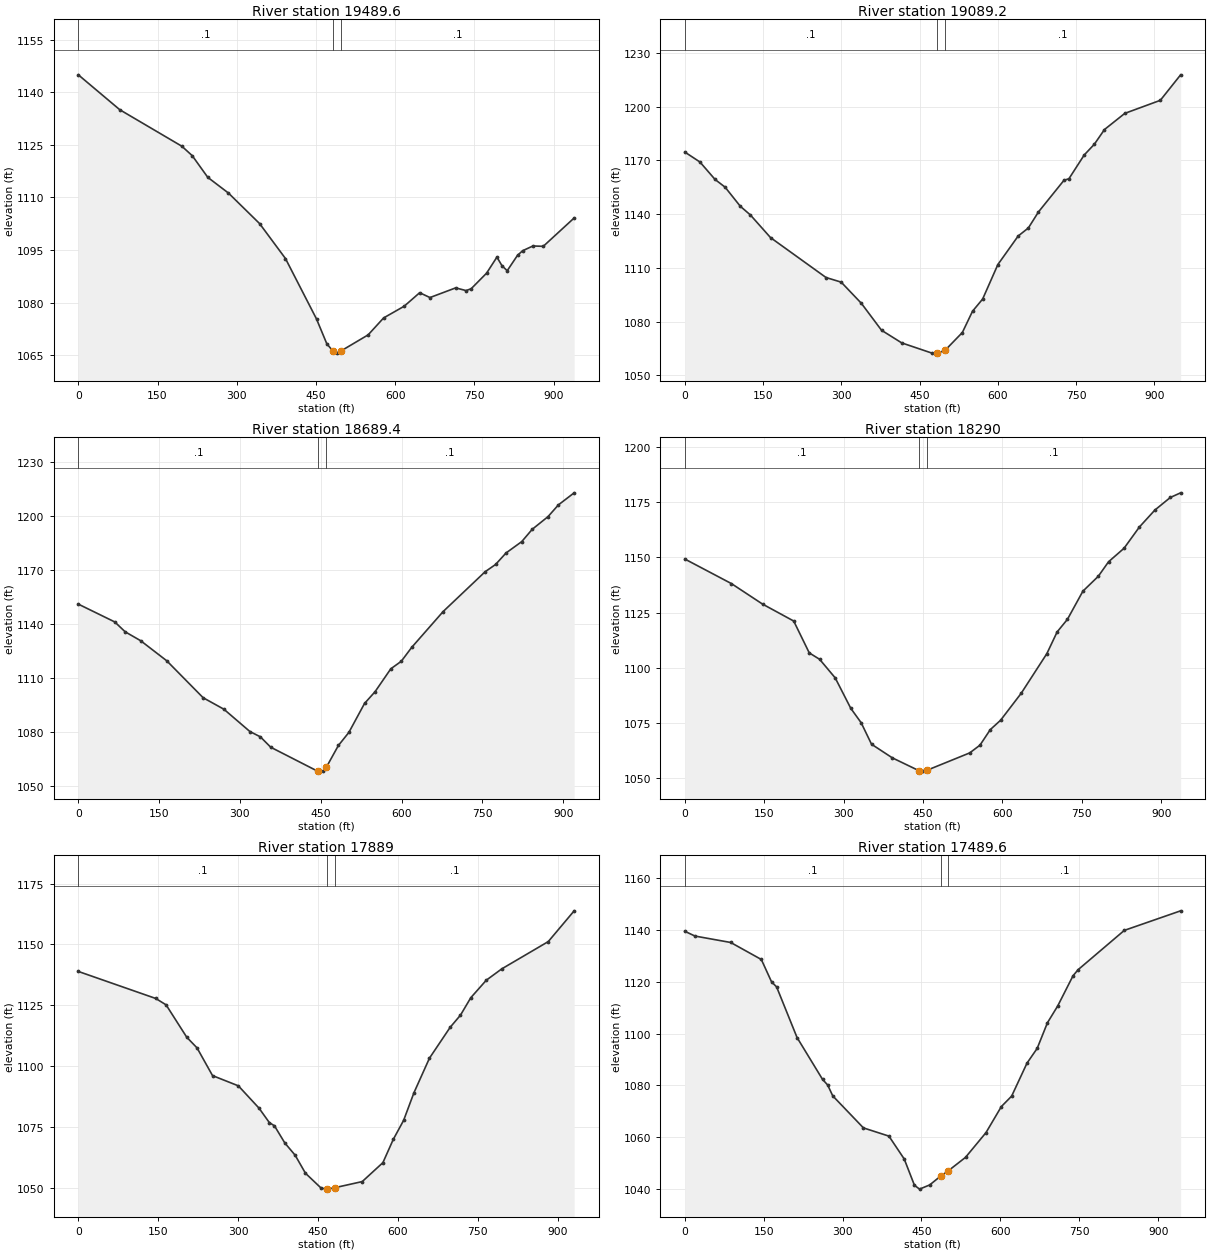
Type RM Length L Ch R = 1 ,19489.6 ,371.659,400.348,415.861
XS GIS Cut Line= 3
     1752571.974      382520.772     1752281.429      382125.758
      1751908.04      381876.827
#Sta/Elev= 30
       0 1144.99    78.5 1135.03   196.1 1124.61   215.8 1121.91   245.2 1115.73
   284.4 1111.24   343.3 1102.54   392.3 1092.57   451.1 1075.32   470.7 1068.21
     482 1066.22   490.4 1065.57     497 1066.15   548.9 1070.78   578.2 1075.61
   617.2 1078.96   646.5 1082.81     666 1081.43   714.7 1084.19   734.3 1083.42
     744 1083.94   773.3  1088.4   792.8 1092.97   802.5 1090.49   812.3 1089.09
   831.8 1093.48   841.6  1094.8   861.1 1096.15   880.6 1096.05   939.1 1104.14
#Mann= 3 , 0 , 0
       0      .1       0     482    .045       0     497      .1       0
Bank Sta=482,497
XS Rating Curve= 0 ,0
Exp/Cntr=0.3,0.1

Type RM Length L Ch R = 1 ,19089.2 ,400.25,399.81,389.749
XS GIS Cut Line= 3
     1752867.008      382352.621     1752544.168      381979.999
     1752387.988      381550.316
#Sta/Elev= 30
       0  1174.6      29 1169.04      58  1159.3    77.3 1154.98   106.3 1144.36
   125.7 1139.49   164.3 1126.86   270.7 1104.58   299.7 1102.01   338.3 1090.22
     377 1075.16   415.7 1068.11   473.7  1062.4   483.6 1062.42   498.6 1063.91
   531.9  1073.9   551.4 1085.78   570.8 1092.58     600 1111.84   638.9 1127.75
   658.4 1132.23   677.8 1141.19   726.5 1158.78   736.2 1159.73   765.4 1172.94
   784.8 1178.94   804.3 1187.16   843.2 1196.17   911.3 1203.46   950.2 1217.68
#Mann= 3 , 0 , 0
       0      .1       0   483.6    .045       0   498.6      .1       0
Bank Sta=483.6,498.6
XS Rating Curve= 0 ,0
Exp/Cntr=0.3,0.1

Type RM Length L Ch R = 1 ,18689.4 ,386.718,399.36,403.123
XS GIS Cut Line= 3
     1753178.753      382089.993     1752849.671      381777.873
     1752535.703      381432.537
#Sta/Elev= 30
       0 1151.07    67.6  1141.2    86.9 1135.73   115.8 1130.76   164.1 1119.65
   231.6 1099.17   270.2 1092.78   318.5  1080.4   337.8 1077.49   357.1 1071.71
   443.9 1058.45   445.2 1058.45   453.6 1058.47   460.2 1060.52   482.7 1072.67
   502.2 1079.95   531.3 1096.02   550.8 1102.51     580 1115.21   599.4 1119.36
   618.9 1127.13   677.2 1146.98     755 1169.02   774.4 1173.05   793.9 1179.45
     823 1185.74   842.5 1192.58   871.7 1199.57   891.1 1206.12   920.3  1212.8
#Mann= 3 , 0 , 0
       0      .1       0   445.2    .045       0   460.2      .1       0
Bank Sta=445.2,460.2
XS Rating Curve= 0 ,0
Exp/Cntr=0.3,0.1

Type RM Length L Ch R = 1 ,18290   ,416.713,401.059,389.655
XS GIS Cut Line= 3
     1753303.749       382016.27     1753172.935      381585.033
     1752909.426      381176.875
#Sta/Elev= 30
       0 1149.19    88.2 1138.06   146.9 1128.81   205.7 1121.16   235.1 1106.76
   254.7 1103.86   284.1 1095.46   313.5 1081.71   333.1  1075.2   352.7 1065.49
   391.9 1059.34   441.6 1053.61   450.6 1053.33   456.6 1053.64   538.1 1061.56
   557.5 1065.06     577 1072.09   596.4 1076.31   635.3 1088.48   683.8 1106.41
   703.3 1116.25   722.7 1121.93   751.9 1134.65     781 1141.38   800.4 1147.95
   829.6 1154.04   858.7 1163.67   887.9 1171.32     917 1176.99   936.5  1179.1
#Mann= 3 , 0 , 0
       0      .1       0   441.6    .045       0   456.6      .1       0
Bank Sta=441.6,456.6
XS Rating Curve= 0 ,0
Exp/Cntr=0.3,0.1

Type RM Length L Ch R = 1 ,17889   ,390.149,399.327,409.428
XS GIS Cut Line= 3
     1753794.547      381544.072     1753389.681      381295.812
     1752979.859      381095.785
#Sta/Elev= 30
       0 1138.92   145.4 1127.82   164.8  1125.2   203.5 1111.93   222.9 1107.53
     252 1096.15   300.5 1091.95   339.2 1082.81   358.6 1076.88   368.3 1075.52
   387.7  1068.5   407.1 1063.47   426.5 1056.06   455.5 1050.04   465.2 1049.54
   467.5 1049.61   482.5 1050.17   533.1 1052.64   571.9 1060.42   591.4 1069.98
   610.8 1077.78   630.2 1089.13   659.3 1103.31   698.1 1115.96   717.5 1120.96
   736.9 1128.13     766 1135.32   795.1 1139.98   882.4 1151.18     931 1163.81
#Mann= 3 , 0 , 0
       0      .1       0   467.5    .045       0   482.5      .1       0
Bank Sta=467.5,482.5
XS Rating Curve= 0 ,0
Exp/Cntr=0.3,0.1

Type RM Length L Ch R = 1 ,17489.6 ,405.617,406.215,408.703
XS GIS Cut Line= 3
     1753925.421      381416.341     1753649.075       381005.92
     1753364.946      380659.707
#Sta/Elev= 30
       0 1139.53    19.4 1137.68    87.3  1135.2   145.5 1128.63   164.9 1120.01
   174.6 1118.02   213.4 1098.48   261.9  1082.3   271.6 1080.14   281.3 1075.93
   339.6 1063.56   388.1 1060.38   417.2 1051.54   436.6  1041.4   446.3  1039.9
   465.7 1041.53   486.2  1044.9   501.2 1047.02   533.7 1052.17   572.7 1061.75
   601.9 1071.81   621.4 1075.83   650.6 1088.57     670 1094.29   689.5 1104.19
     709 1110.67   738.2 1122.36   747.9  1124.7   835.6 1139.87   942.7 1147.43
#Mann= 3 , 0 , 0
       0      .1       0   486.2    .045       0   501.2      .1       0
Bank Sta=486.2,501.2
XS Rating Curve= 0 ,0
Exp/Cntr=0.3,0.1

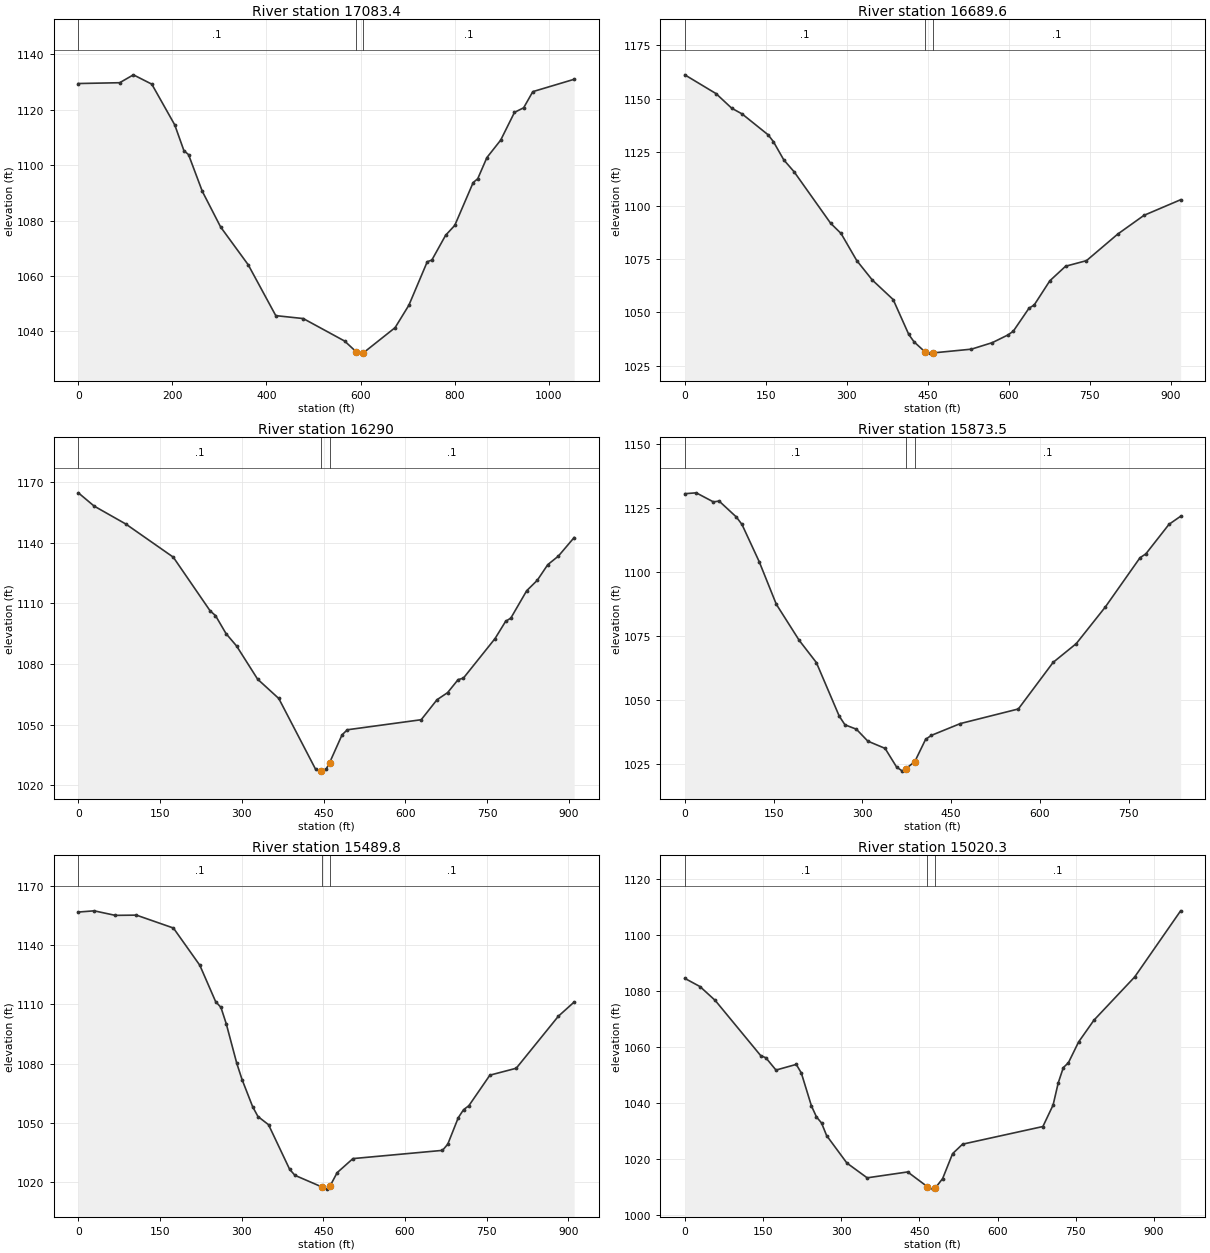
Type RM Length L Ch R = 1 ,17083.4 ,394.569,393.808,397.786
XS GIS Cut Line= 3
     1754099.574      381425.819     1754075.598      380938.309
      1753758.93      380469.103
#Sta/Elev= 30
       0 1129.48    87.9 1129.77   117.1 1132.62   156.2 1129.25     205 1114.54
   224.5 1105.24   234.3 1103.81   263.6 1090.55   302.6 1077.66   361.2 1064.03
   419.8 1045.67   478.3 1044.61   566.2 1036.49   590.4 1032.68   605.2 1032.13
   605.4 1032.15   673.5 1041.33   702.8 1049.44   741.9 1065.14   751.6 1065.73
   780.9 1074.69   800.4 1078.27   839.5 1093.73   849.2  1095.1   868.7 1102.75
     898 1109.05   927.3 1119.06   946.8 1120.72   966.3 1126.55  1054.2 1131.01
#Mann= 3 , 0 , 0
       0      .1       0   590.4    .045       0   605.4      .1       0
Bank Sta=590.4,605.4
XS Rating Curve= 0 ,0
Exp/Cntr=0.3,0.1

Type RM Length L Ch R = 1 ,16689.6 ,393.816,399.664,400.55
XS GIS Cut Line= 3
     1754636.843      381068.599     1754373.369      380699.737
     1754191.861      380271.996
#Sta/Elev= 30
       0 1161.23    57.9 1152.42    86.8  1145.6   106.1 1142.91   154.3 1133.12
     164 1129.95   183.2 1121.41   202.5 1115.77     270 1091.69   289.3  1086.9
   318.3 1074.23   347.2 1065.08   385.8 1055.94   414.7 1039.58   424.4 1036.14
   444.6 1031.45   453.3 1030.84   459.6 1030.94   530.7  1032.7   569.5 1035.77
   598.5 1039.38   608.2 1041.12   637.2 1051.86   646.9  1053.4   675.9 1064.75
     705 1071.55   743.7 1074.17   801.8 1086.66   850.2  1095.4     918 1102.71
#Mann= 3 , 0 , 0
       0      .1       0   444.6    .045       0   459.6      .1       0
Bank Sta=444.6,459.6
XS Rating Curve= 0 ,0
Exp/Cntr=0.3,0.1

Type RM Length L Ch R = 1 ,16290   ,419.846,416.458,413.292
XS GIS Cut Line= 3
     1754889.591      380946.766     1754728.951      380521.072
     1754563.838      380097.055
#Sta/Elev= 30
       0 1164.61      29 1158.06    87.1  1149.2   174.3  1132.8     242 1106.23
   251.7 1103.95   271.1 1095.02   290.4 1088.92   329.1 1072.49   367.9 1062.95
   435.6  1027.9   445.3 1027.05   446.1 1027.14     455 1028.11   461.1  1031.2
     484 1044.98   493.7 1047.49   629.3 1052.46   658.3 1062.35   677.7 1065.84
     697 1072.27   706.7 1073.01   764.8 1092.58   784.2 1101.08   793.8 1102.71
   822.9 1116.23   842.3 1121.38   861.6 1129.12     881 1133.32     910 1142.52
#Mann= 3 , 0 , 0
       0      .1       0   446.1    .045       0   461.1      .1       0
Bank Sta=446.1,461.1
XS Rating Curve= 0 ,0
Exp/Cntr=0.3,0.1

Type RM Length L Ch R = 1 ,15873.5 ,383.689,383.729,382.659
XS GIS Cut Line= 3
     1755364.938      380578.302      1755114.37      380365.767
     1754867.829      379920.326
#Sta/Elev= 30
       0 1130.55    19.3 1130.89    48.3 1127.35      58 1127.67      87 1121.46
    96.6 1118.53   125.6 1104.03   154.6 1087.33   193.3 1073.21   222.3 1064.53
   260.9  1043.6   270.6 1040.19   289.9 1038.47   309.2 1033.81   338.4 1030.97
   357.9 1023.65   367.7 1022.08   373.5 1023.05   388.5 1025.76   406.9 1034.53
   416.7 1036.07   465.6 1040.68   563.5 1046.38   622.3  1064.6   661.4 1071.94
   710.4 1086.23   769.1 1105.52   778.9 1107.01   818.1 1118.58   837.7 1121.73
#Mann= 3 , 0 , 0
       0      .1       0   373.5    .045       0   388.5      .1       0
Bank Sta=373.5,388.5
XS Rating Curve= 0 ,0
Exp/Cntr=0.3,0.1

Type RM Length L Ch R = 1 ,15489.8 ,490.07,469.501,446.881
XS GIS Cut Line= 3
     1755619.124       380505.86      1755400.66      380105.469
     1755162.299      379718.132
#Sta/Elev= 30
       0 1156.82    29.1 1157.44    67.9 1155.14   106.7 1155.26   174.7 1148.72
   223.2 1129.85   252.3  1111.4     262 1108.51   271.7 1100.25   291.1 1080.15
   300.8 1071.93   320.2 1058.21     330 1053.21   349.4 1049.07   388.2 1026.47
   397.9 1023.42   447.4 1017.53   456.1 1016.42   462.4 1017.98   475.5 1024.77
   504.5 1031.89     669 1036.06   678.7  1039.2     698 1052.61   707.7 1056.67
   717.4 1058.67   756.1 1074.17   804.5 1077.67   881.9 1104.04   910.9 1111.23
#Mann= 3 , 0 , 0
       0      .1       0   447.4    .045       0   462.4      .1       0
Bank Sta=447.4,462.4
XS Rating Curve= 0 ,0
Exp/Cntr=0.3,0.1

Type RM Length L Ch R = 1 ,15020.3 ,328.243,331.263,337.066
XS GIS Cut Line= 4
     1756103.071      379980.651     1755689.018      379812.399
     1755512.594      379770.668     1755199.384      379692.365
#Sta/Elev= 30
       0 1084.46    29.1 1081.54    58.3  1076.6   145.7 1056.88   155.5 1056.14
   174.9 1051.75   213.8 1053.77   223.5 1050.72   242.9 1038.97   252.6 1035.03
   262.3 1032.88     272  1028.4   310.9 1018.59   349.8 1013.31   427.5 1015.41
   465.3 1010.15   475.6 1009.28   480.3 1009.64   494.6 1013.05   513.7 1021.94
   532.8 1025.31   686.9 1031.61   706.5 1039.29   716.3 1047.17   726.1 1052.63
   735.8 1054.35   755.4 1061.77   784.8 1069.54     863 1084.97   951.1 1108.55
#Mann= 3 , 0 , 0
       0      .1       0   465.3    .045       0   480.3      .1       0
Bank Sta=465.3,480.3
XS Rating Curve= 0 ,0
Exp/Cntr=0.3,0.1

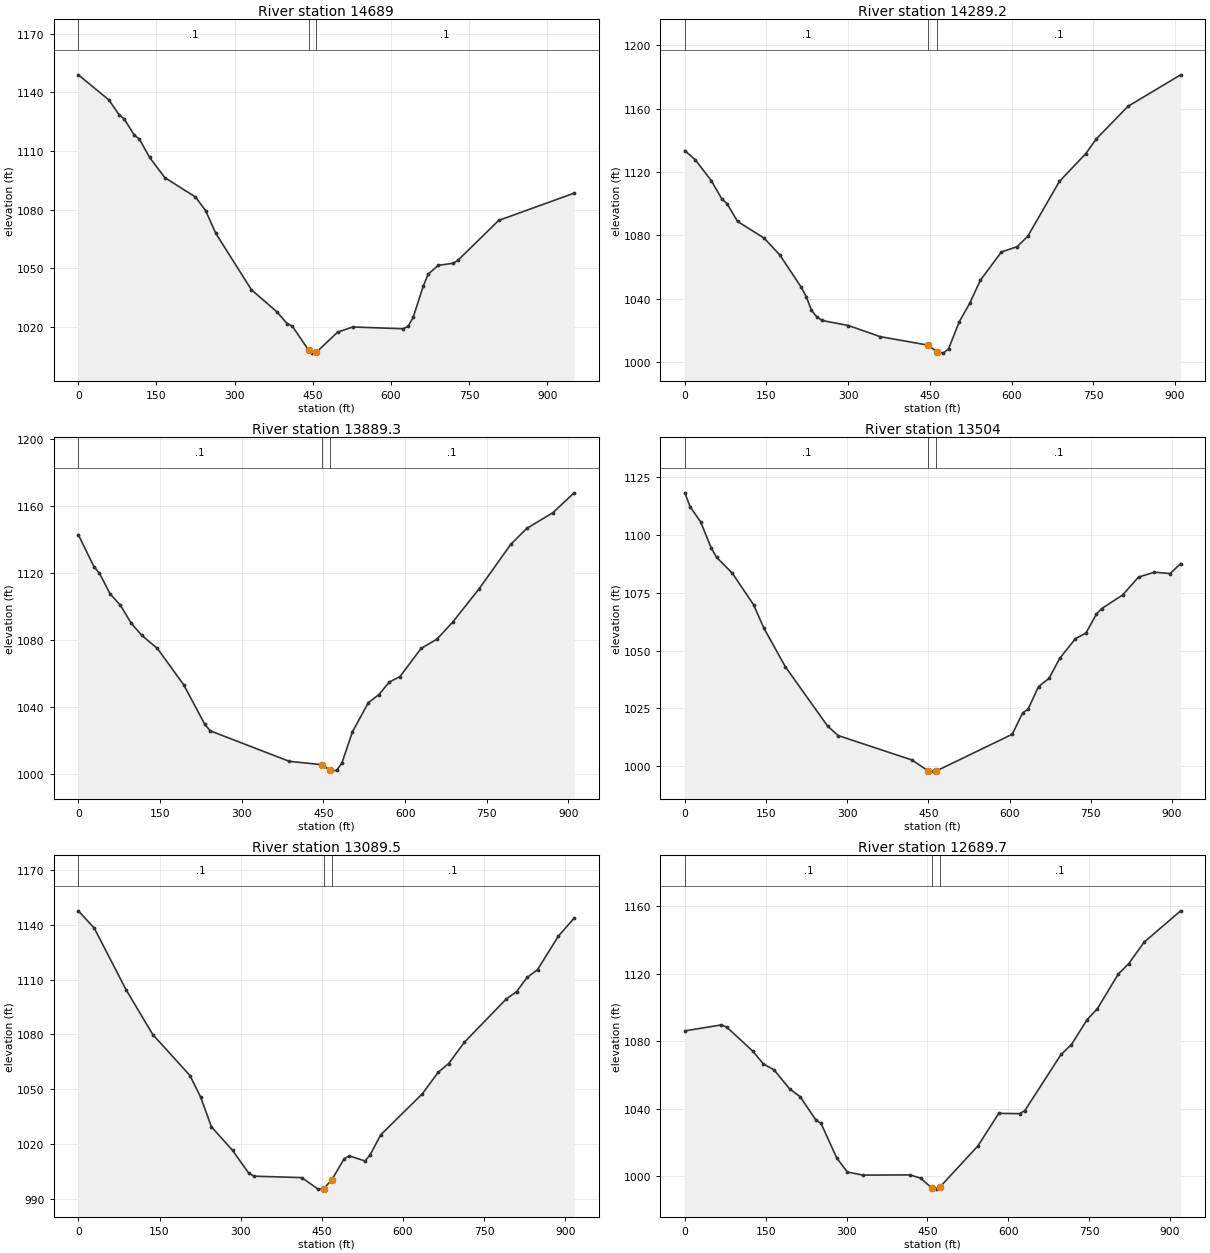
Type RM Length L Ch R = 1 ,14689   ,397.765,399.85,400.075
XS GIS Cut Line= 3
     1756246.636      379684.427     1755825.998       379526.11
     1755371.649      379312.039
#Sta/Elev= 30
       0 1148.96    58.6 1136.14    78.2  1128.5    87.9 1126.45   107.5 1118.05
   117.2  1116.1   136.8 1106.68   166.1 1096.32   224.7 1086.47   244.3 1079.52
   263.8 1067.86   332.2 1038.97   381.1 1027.71   400.6 1021.69   410.4 1020.46
   441.8 1008.17   449.4 1006.54   456.8 1006.98   497.7 1017.29   526.7 1019.92
   623.3 1019.02     633  1020.2   642.6 1024.81   661.9 1040.74   671.6 1046.99
   690.9 1051.47   719.9 1052.55   729.5 1054.27   806.8 1074.45   951.7 1088.41
#Mann= 3 , 0 , 0
       0      .1       0   441.8    .045       0   456.8      .1       0
Bank Sta=441.8,456.8
XS Rating Curve= 0 ,0
Exp/Cntr=0.3,0.1

Type RM Length L Ch R = 1 ,14289.2 ,396.791,399.896,401.156
XS GIS Cut Line= 3
     1756295.446       379346.16     1755887.331       379143.88
     1755488.637      378924.817
#Sta/Elev= 30
       0 1133.46    19.4 1127.61    48.5  1114.6    67.8  1103.1    77.5 1099.98
    96.9 1088.78   145.4 1078.32   174.4 1067.68   213.2 1047.56   222.9 1041.43
   232.6 1032.67   242.3 1028.65     252 1026.31   300.4 1023.12   358.6 1016.13
   447.3  1010.7   462.3 1006.71   474.9 1005.71   484.5  1008.6   503.9 1025.46
   523.2  1037.2   542.6 1051.62   581.3 1069.51   610.4  1072.9   629.7 1079.44
   687.8 1114.01   736.2 1131.54   755.5  1140.8   813.6 1161.36   910.4 1181.26
#Mann= 3 , 0 , 0
       0      .1       0   447.3    .045       0   462.3      .1       0
Bank Sta=447.3,462.3
XS Rating Curve= 0 ,0
Exp/Cntr=0.3,0.1

Type RM Length L Ch R = 1 ,13889.3 ,378.893,385.232,392.495
XS GIS Cut Line= 3
     1756463.237       379054.37     1756087.262      378798.271
      1755700.21      378558.118
#Sta/Elev= 30
       0 1142.83      29 1123.58    38.7 1119.91    58.1 1107.69    77.4 1100.75
    96.8  1090.2   116.1 1082.96   145.2 1075.05   193.6 1053.29   232.3  1029.8
     242 1025.97   387.2 1007.77   446.6 1005.79   461.6 1002.57   464.6 1001.92
   474.3 1002.43     484 1006.84   503.4 1025.44   532.4 1042.66   551.8 1047.53
   571.2 1055.04   590.6  1058.3   629.4 1075.08   658.4 1080.53   687.5  1090.8
     736 1110.63   794.1 1137.13   823.2 1146.53   871.6 1156.02   910.4 1167.79
#Mann= 3 , 0 , 0
       0      .1       0   446.6    .045       0   461.6      .1       0
Bank Sta=446.6,461.6
XS Rating Curve= 0 ,0
Exp/Cntr=0.3,0.1

Type RM Length L Ch R = 1 ,13504   ,414.336,414.489,411.056
XS GIS Cut Line= 3
     1756593.827       378838.39     1756273.247      378457.423
      1755917.53      378238.176
#Sta/Elev= 30
       0 1118.31     9.8  1112.3    29.3 1105.72    48.8 1094.42    58.6 1090.42
    87.9 1083.46   126.9 1069.87   146.4 1059.56   185.5 1043.07   263.6 1017.31
   283.1 1013.18   419.8 1002.56   449.5  997.84   458.9  997.75   464.5  997.81
   604.8 1013.72   624.2 1023.07   633.9 1024.51   653.4 1034.39   672.8 1037.95
   692.3 1046.55   721.4 1055.11   740.8 1057.52   760.3 1065.77     770 1068.16
   808.9  1074.1     838 1081.81   867.2 1083.92   896.3 1083.35   915.8 1087.61
#Mann= 3 , 0 , 0
       0      .1       0   449.5    .045       0   464.5      .1       0
Bank Sta=449.5,464.5
XS Rating Curve= 0 ,0
Exp/Cntr=0.3,0.1

Type RM Length L Ch R = 1 ,13089.5 ,397.509,399.871,400.661
XS GIS Cut Line= 3
     1756840.724      378548.152      1756552.97      378186.667
     1756221.516      377876.041
#Sta/Elev= 30
       0 1147.51    29.5 1138.03    88.5 1104.27   137.6 1079.98   206.4 1057.57
   226.1  1045.8   245.8  1029.7   285.1 1016.68   314.6 1004.46   324.4 1002.66
   412.9 1001.88   442.4  995.74   452.2  995.59   453.6  995.88   468.6  1000.8
     491 1012.06   500.7 1013.75   529.7 1010.97   539.4 1014.35   558.7 1025.21
     636 1047.71     665 1059.37   684.3 1064.11   713.3 1075.73   790.6 1099.33
     810 1103.45   829.3 1111.13   848.6 1115.41   887.3 1133.77   916.3 1143.54
#Mann= 3 , 0 , 0
       0      .1       0   453.6    .045       0   468.6      .1       0
Bank Sta=453.6,468.6
XS Rating Curve= 0 ,0
Exp/Cntr=0.3,0.1

Type RM Length L Ch R = 1 ,12689.7 ,457.396,462.571,472.525
XS GIS Cut Line= 3
     1757131.199      378363.325     1756880.889      377969.609
     1756560.597      377649.316
#Sta/Elev= 30
       0 1086.18      68 1089.71    77.8 1088.44   126.4 1074.04   145.8 1066.51
   165.2 1063.14   194.4 1051.74   213.8 1047.13     243 1033.32   252.7 1031.23
   281.9 1010.69   301.3 1002.41   330.5 1000.55   417.9 1000.69   437.4  998.74
     458  992.92   466.5  992.24     473  993.44   543.6 1017.91   582.2 1037.21
   620.7 1037.05   630.4 1038.79   697.8 1072.18   717.1 1078.08     746 1092.81
   765.3 1099.41   803.9 1119.91   823.1 1126.04     852 1138.88   919.5 1157.43
#Mann= 3 , 0 , 0
       0      .1       0     458    .045       0     473      .1       0
Bank Sta=458,473
XS Rating Curve= 0 ,0
Exp/Cntr=0.3,0.1

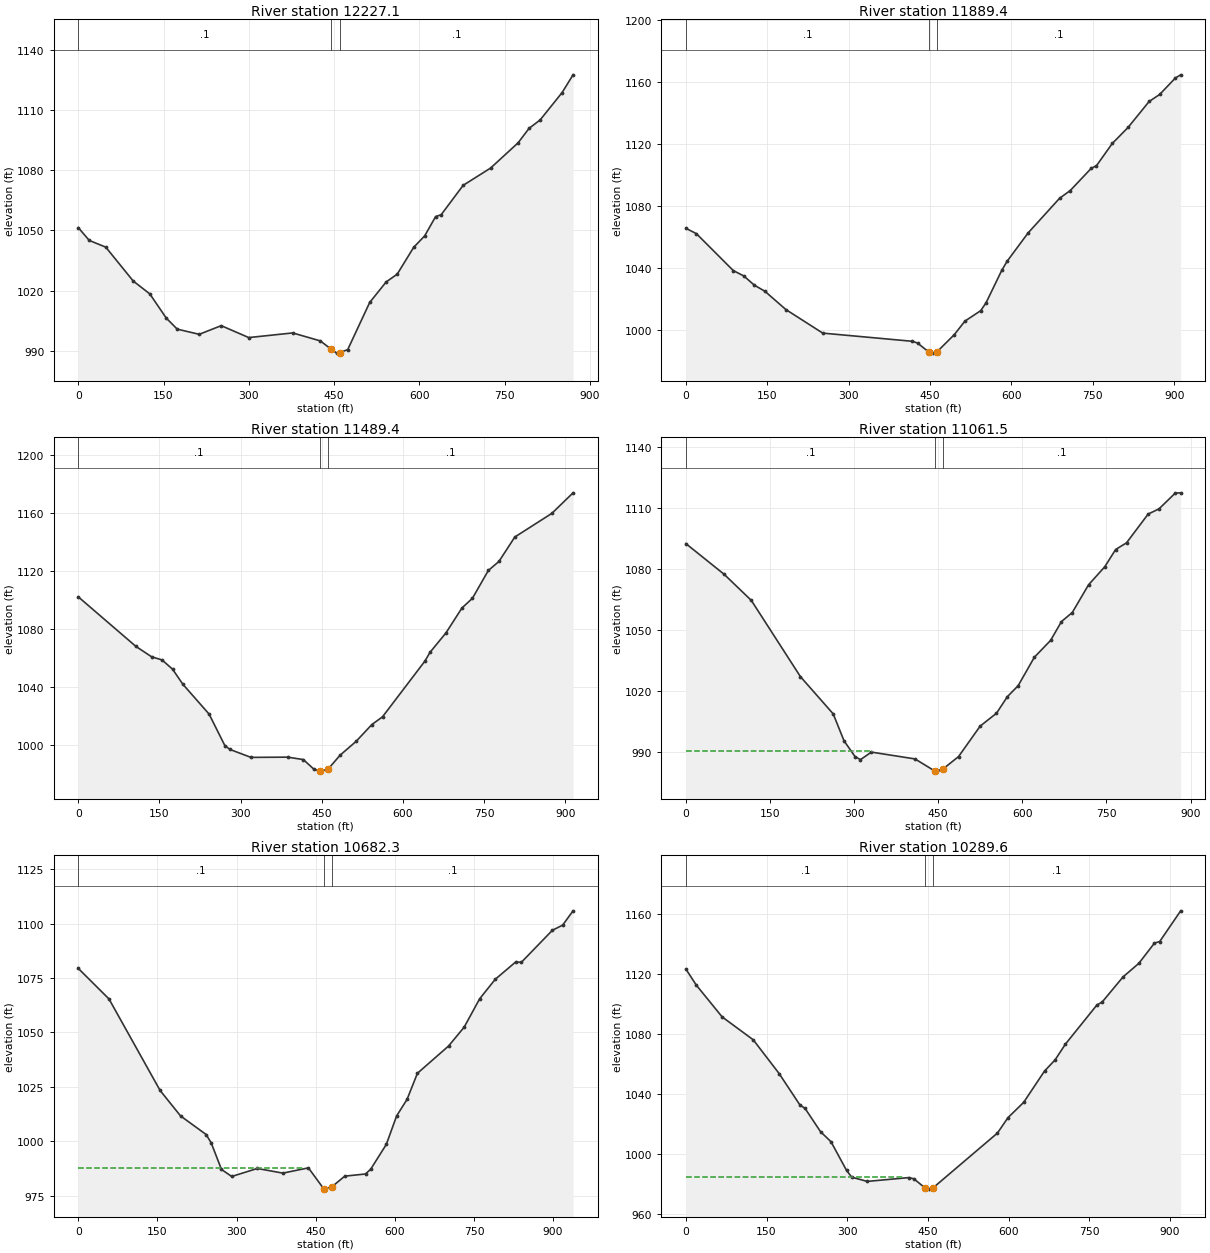
Type RM Length L Ch R = 1 ,12227.1 ,347.859,337.663,327.173
XS GIS Cut Line= 3
     1757444.701      378194.188     1757286.705      377819.817
     1757134.574      377381.323
#Sta/Elev= 30
       0 1051.39    19.3    1045    48.4 1041.64    96.7 1024.74   125.8 1018.34
   154.8 1006.27   174.1 1000.75   212.8  998.17   251.5 1002.49   299.9  996.55
   377.3  998.86   425.7   994.9   444.6  990.85   454.7  988.79   459.6  989.03
     474  990.53   512.7 1014.05   541.7  1024.3   561.1 1028.17   590.1 1041.56
   609.4 1047.25   628.7  1056.9   638.4  1057.8   677.1 1072.47   725.4 1081.09
   773.8 1093.68   793.1  1100.9   812.5 1105.07   851.1  1118.7   870.5 1127.59
#Mann= 3 , 0 , 0
       0      .1       0   444.6    .045       0   459.6      .1       0
Bank Sta=444.6,459.6
XS Rating Curve= 0 ,0
Exp/Cntr=0.3,0.1

Type RM Length L Ch R = 1 ,11889.4 ,401.261,400.049,401.446
XS GIS Cut Line= 3
     1757862.504       377897.08     1757540.305      377574.283
     1757213.862      377256.023
#Sta/Elev= 30
       0 1065.75    19.4 1062.27    87.3 1038.51   106.7 1035.03   126.1  1029.1
   145.6 1025.17   184.4 1013.34   252.3  998.18   417.3  992.91     427  991.77
   447.6  986.04   456.1  985.28   462.6  986.03   494.9  997.26   514.3 1005.91
   543.4 1012.65   553.1 1017.61   582.2 1038.62   591.9 1044.41   630.7 1062.72
   688.9 1085.13   708.3 1090.03   747.1 1104.38   756.8 1106.09   785.9  1120.4
     815 1130.74   853.8 1147.47   873.2 1151.98   902.3 1162.63     912 1164.66
#Mann= 3 , 0 , 0
       0      .1       0   447.6    .045       0   462.6      .1       0
Bank Sta=447.6,462.6
XS Rating Curve= 0 ,0
Exp/Cntr=0.3,0.1

Type RM Length L Ch R = 1 ,11489.4 ,422.371,427.866,430.449
XS GIS Cut Line= 3
     1758181.918      377630.214     1757845.099      377325.083
     1757539.181      376981.979
#Sta/Elev= 30
       0 1101.99   106.4 1067.86   135.4  1060.7   154.7 1058.51   174.1 1052.18
   193.4 1041.67   241.7 1021.18   270.8  999.48   280.4  996.79   319.1  991.34
   386.8  991.51   415.8  989.84   435.1  983.28   444.8  981.87     446  981.87
     461  983.03   483.8  992.87   513.2 1002.34   542.5 1013.99   562.1 1019.29
   640.3 1057.63   650.1 1063.86   679.4 1077.17   708.8 1094.27   728.3 1101.03
   757.7 1120.19   777.2 1126.37   806.6 1143.24     875 1159.53   914.2 1173.69
#Mann= 3 , 0 , 0
       0      .1       0     446    .045       0     461      .1       0
Bank Sta=446,461
XS Rating Curve= 0 ,0
Exp/Cntr=0.3,0.1

Type RM Length L Ch R = 1 ,11061.5 ,386.147,379.256,372.961
XS GIS Cut Line= 3
     1758404.632      377408.037       1758142.3      377033.506
     1757886.838      376693.729
#Sta/Elev= 30
       0 1092.47    68.1 1077.38   116.7 1064.48   204.3 1026.91   262.7 1008.59
   282.1  995.26   301.6  987.57   311.3  986.03   330.8  989.75   408.6  986.38
   444.1  980.39   447.5  980.37   459.1  981.56   486.2  987.52   524.9 1002.58
   553.9 1008.88   573.2 1017.01   592.5 1022.45   621.5 1036.49   650.5 1044.81
   669.8 1054.06   689.1 1058.52   718.1 1072.17   747.1 1081.09   766.4 1089.56
   785.8 1092.85   824.4 1107.03   843.7 1109.58   872.7 1117.34   882.4 1117.49
#Mann= 3 , 0 , 0
       0      .1       0   444.1    .045       0   459.1      .1       0
#XS Ineff= 2 , 0
          332.15  990.13
Permanent Ineff=
       F       F
Bank Sta=444.1,459.1
XS Rating Curve= 0 ,0
Exp/Cntr=0.3,0.1

Type RM Length L Ch R = 1 ,10682.3 ,384.662,392.633,397.69
XS GIS Cut Line= 3
     1758738.657      377003.233     1758378.466       376757.14
     1757976.868      376456.633
#Sta/Elev= 30
       0 1079.42    58.2  1065.4   155.1 1023.38   193.9 1011.69   242.4 1003.16
     252  999.29   271.4  987.14   290.8  983.91   339.3  987.58   387.8  985.45
   436.2  987.86   465.7   978.1   465.8   978.1   480.8   979.2   505.1  984.06
   544.4  985.05   554.3  987.27   583.8  998.61   603.4 1011.71   623.1 1019.28
   642.8 1031.28   701.8 1043.79   731.3 1052.42   760.8 1065.49   790.3 1074.42
   829.6 1082.49   839.5 1082.14   898.5  1096.9   918.1  1099.3   937.8 1105.85
#Mann= 3 , 0 , 0
       0      .1       0   465.8    .045       0   480.8      .1       0
#XS Ineff= 2 , 0
          427.81  987.79
Permanent Ineff=
       F       F
Bank Sta=465.8,480.8
XS Rating Curve= 0 ,0
Exp/Cntr=0.3,0.1

Type RM Length L Ch R = 1 ,10289.6 ,413.806,406.772,402.652
XS GIS Cut Line= 3
     1758906.113      376867.814     1758645.506      376497.478
     1758327.295      376155.352
#Sta/Elev= 30
       0  1123.4    19.3 1112.74    67.4 1091.55   125.3 1076.28   173.4 1053.82
     212 1032.93   221.6 1030.63   250.5 1015.06   269.8 1008.47   298.7  989.37
   308.3  984.84   337.2  982.01   414.3  984.55   423.9  983.76   444.1  977.84
   452.8  976.87   459.1  977.57   579.4 1014.21   598.9 1024.43   628.1 1034.63
     667 1055.54   686.5  1062.9   705.9 1073.48   764.3 1099.47   774.1 1101.45
     813  1118.2   842.2 1127.18   871.4 1140.71   881.1 1141.74   920.1 1162.18
#Mann= 3 , 0 , 0
       0      .1       0   444.1    .045       0   459.1      .1       0
#XS Ineff= 2 , 0
          403.01  984.87
Permanent Ineff=
       F       F
Bank Sta=444.1,459.1
XS Rating Curve= 0 ,0
Exp/Cntr=0.3,0.1

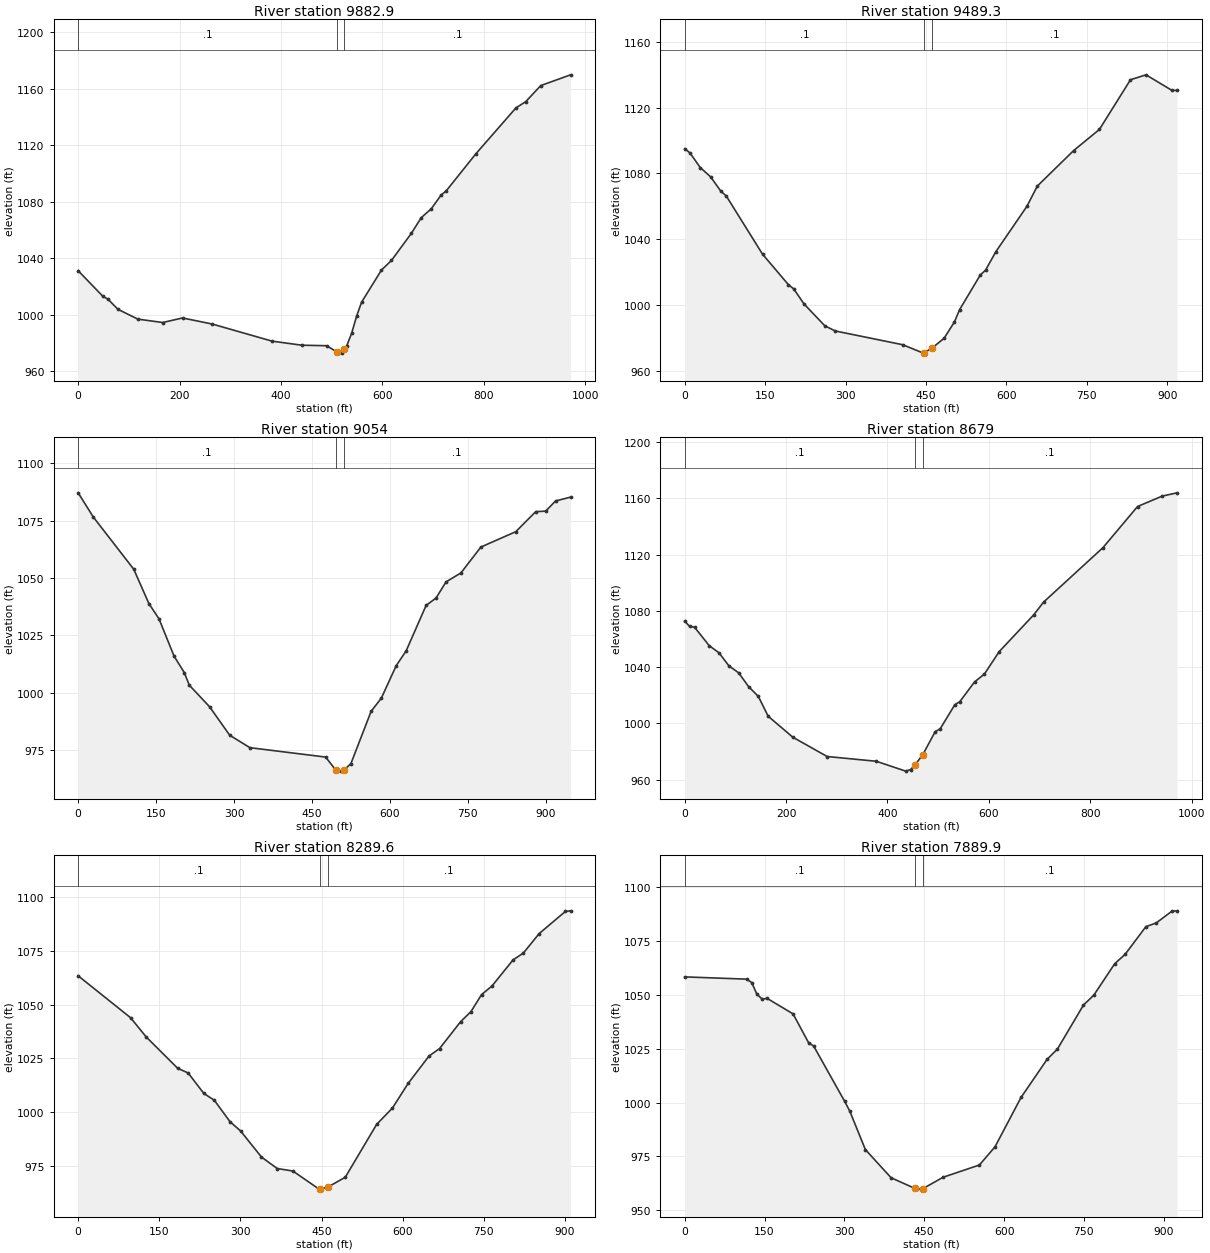
Type RM Length L Ch R = 1 ,9882.9  ,393.795,393.568,390.187
XS GIS Cut Line= 3
     1759318.096      376390.237     1758881.839      376188.887
     1758490.782      375892.529
#Sta/Elev= 30
       0 1031.23      49 1013.03    58.8 1011.11    78.4 1003.94   117.7  996.97
   166.7  994.58   205.9   997.8   264.8  993.46   382.4  981.39   441.3  978.52
   490.3  978.16   509.8  973.81   519.7  972.92   524.8  975.53   529.5  977.93
   539.4     987   549.2  999.13     559    1009   598.2 1031.71   617.9 1038.51
   657.1 1057.65   676.7 1068.79   696.4 1075.05     716 1084.84   725.8 1087.69
   784.7  1114.1   863.2 1146.35   882.8 1150.88   912.3  1162.2   971.1 1169.82
#Mann= 3 , 0 , 0
       0      .1       0   509.8    .045       0   524.8      .1       0
Bank Sta=509.8,524.8
XS Rating Curve= 0 ,0
Exp/Cntr=0.3,0.1

Type RM Length L Ch R = 1 ,9489.3  ,430.88,435.336,442.945
XS GIS Cut Line= 3
     1759448.918      376125.419     1759083.297      375854.776
     1758675.245      375634.881
#Sta/Elev= 30
       0 1094.91     9.7 1092.53      29 1083.52    48.4 1077.87    67.7 1069.04
    77.4 1066.32   145.2 1030.86   193.6 1012.27   203.2 1009.83   222.6 1000.61
   261.3  987.34   280.7  984.19   406.5  975.83   445.2  970.71   446.4  970.86
   461.4  973.78   483.9  979.75   503.2  989.71   512.8  997.16   551.5 1018.27
   561.1  1021.1   580.4 1032.37   638.4 1059.99   657.7 1072.26   725.3 1093.79
   773.6  1106.7   831.5  1136.9   860.5 1139.88   908.8 1130.41   918.4 1130.43
#Mann= 3 , 0 , 0
       0      .1       0   446.4    .045       0   461.4      .1       0
Bank Sta=446.4,461.4
XS Rating Curve= 0 ,0
Exp/Cntr=0.3,0.1

Type RM Length L Ch R = 1 ,9054    ,363.276,375.002,386.728
XS GIS Cut Line= 3
     1759602.959      375849.227     1759206.235      375421.523
     1758962.379       375150.82
#Sta/Elev= 30
       0 1087.15    29.2 1076.57     107  1053.8   136.1 1038.84   155.6 1032.16
   184.7 1015.83   204.2 1008.73   213.9 1003.21   252.8  993.83   291.7  981.36
   330.6  975.93   476.4  971.83   496.3     966   505.6   965.7   511.3  966.07
     525  969.01   563.9  991.82   583.4   997.5   612.1  1011.7   631.3  1018.2
   669.7 1038.03   688.8 1041.23     708 1048.27   736.8 1052.22   775.1 1063.49
   842.2 1070.18   880.6 1078.93   899.8 1079.16   918.9 1083.61   947.7 1085.27
#Mann= 3 , 0 , 0
       0      .1       0   496.3    .045       0   511.3      .1       0
Bank Sta=496.3,511.3
XS Rating Curve= 0 ,0
Exp/Cntr=0.3,0.1

Type RM Length L Ch R = 1 ,8679    ,398.08,389.331,380.121
XS GIS Cut Line= 3
     1759702.596      375797.094     1759574.069      375240.039
      1759334.31      374920.361
#Sta/Elev= 30
       0 1072.65     9.7 1068.92    19.4 1068.37    48.4 1055.23    67.8 1050.12
    87.2  1040.9   106.6 1035.88     126 1026.14   145.3 1019.15   164.7 1005.07
   213.2  990.19     281  976.44   377.9  973.06     436  966.05   445.7  967.16
   454.6  970.58   469.6  977.71   494.2  994.14   503.9  996.06   532.9 1013.27
   542.6 1015.38   571.7 1029.41   591.2 1035.03   620.4 1050.98   688.6 1077.16
   708.1 1086.23   825.1 1124.89   893.3 1154.11     942 1161.53   971.3 1163.85
#Mann= 3 , 0 , 0
       0      .1       0   454.6    .045       0   469.6      .1       0
Bank Sta=454.6,469.6
XS Rating Curve= 0 ,0
Exp/Cntr=0.3,0.1

Type RM Length L Ch R = 1 ,8289.6  ,405.315,399.699,394.542
XS GIS Cut Line= 3
     1760218.807      375579.022     1759954.357      375208.791
     1759681.883      374844.236
#Sta/Elev= 30
       0 1063.44    96.8 1043.96   125.8 1034.99   183.9 1020.44   203.3 1018.23
   232.3 1008.72   251.7 1005.56   280.7  995.57   300.1  991.31   338.8  979.14
   367.9  973.81   396.9  972.64   445.3  964.22   446.3  964.23   461.3  965.14
   493.7  969.75   551.8  994.37   580.9 1001.94   609.9  1013.4   648.6 1026.15
     668 1029.59   706.8 1042.07   726.1 1046.81   745.5 1054.67   764.9 1058.71
   803.6 1070.77     823 1074.06     852 1083.05   900.4 1093.36   910.1 1093.66
#Mann= 3 , 0 , 0
       0      .1       0   446.3    .045       0   461.3      .1       0
Bank Sta=446.3,461.3
XS Rating Curve= 0 ,0
Exp/Cntr=0.3,0.1

Type RM Length L Ch R = 1 ,7889.9  ,395.285,400.37,410.378
XS GIS Cut Line= 3
     1760557.513      375294.002     1760282.335      374980.792
     1759895.392      374651.486
#Sta/Elev= 30
       0 1058.29   116.4 1057.24     126 1055.66   135.7 1050.23   145.4 1048.01
   155.1 1048.29   203.6 1041.13   232.7 1027.78   242.4 1026.17   300.6 1000.53
   310.3  995.95   339.4   978.2   387.8  965.11   432.1  960.22   436.5  959.84
   447.1     960   485.3  965.33   553.7  971.04     583  979.48   631.9 1002.38
   680.7    1020   700.3 1024.84   749.1  1045.2   768.7 1049.84   807.8 1064.39
   827.3 1068.72   866.4 1081.58   885.9 1083.31   915.3 1088.77     925 1088.93
#Mann= 3 , 0 , 0
       0      .1       0   432.1    .045       0   447.1      .1       0
Bank Sta=432.1,447.1
XS Rating Curve= 0 ,0
Exp/Cntr=0.3,0.1