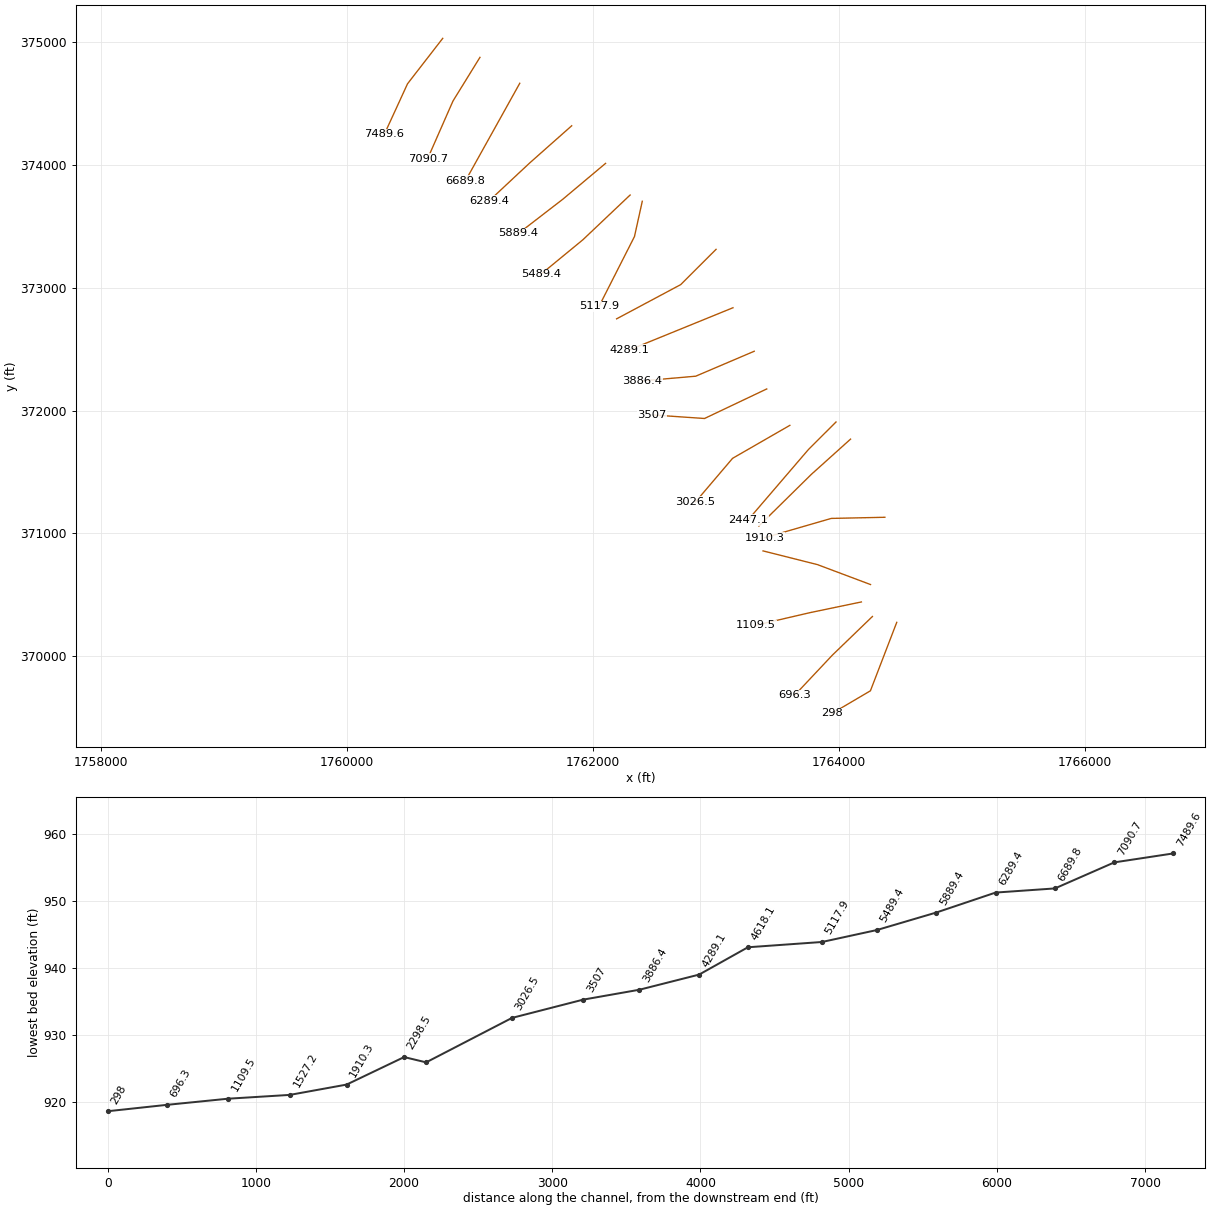
HEC-RAS study DrnkrdMlRn.prj: DrnkrdMlRn

--- DrnkrdMlRn.g01 (geometry) --- (continued)

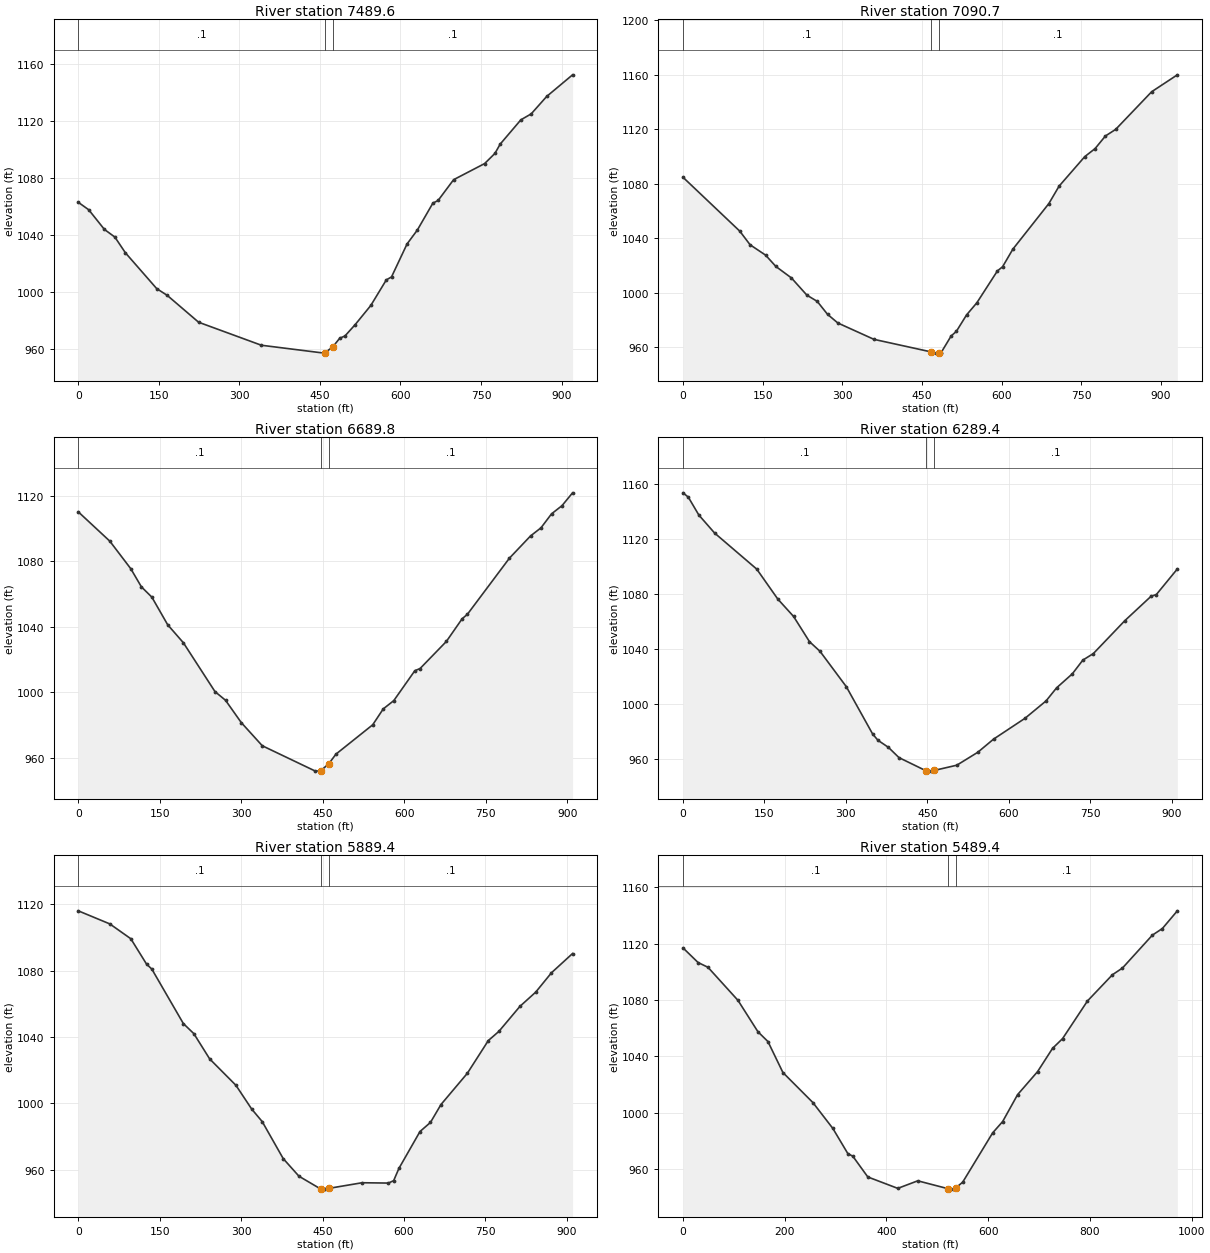
Type RM Length L Ch R = 1 ,7489.6  ,393.234,398.867,399.579
XS GIS Cut Line= 3
     1760780.764      375032.742     1760494.655      374662.804
     1760306.008      374251.212
#Sta/Elev= 30
       0 1063.14    19.5 1057.88    48.7 1044.07    68.2 1038.68    87.7 1027.69
   146.1 1002.46   165.6  997.75   224.1  978.85     341  962.68   457.9  957.14
   458.8  957.27   473.8  961.47   486.9  967.64   496.6  969.19   515.8  977.25
   544.7  990.62   573.6  1008.6   583.3 1010.69   612.2 1033.84   631.4 1043.64
   660.3 1062.54     670  1064.4   698.9 1079.01   756.7 1090.35   775.9 1097.51
   785.6    1104   824.1 1121.07   843.4 1125.28   872.3 1137.54   920.4 1152.71
#Mann= 3 , 0 , 0
       0      .1       0   458.8    .045       0   473.8      .1       0
Bank Sta=458.8,473.8
XS Rating Curve= 0 ,0
Exp/Cntr=0.3,0.1

Type RM Length L Ch R = 1 ,7090.7  ,403.034,400.922,398.811
XS GIS Cut Line= 3
     1761083.258       374877.88     1760864.011      374522.163
     1760657.838      374052.241
#Sta/Elev= 30
       0 1084.73   106.9 1045.24   126.3 1035.25   155.5 1027.66   174.9 1019.34
   204.1 1010.95   233.2  998.34   252.7  993.76   272.1  984.28   291.5  977.91
   359.6   965.9   466.6  956.75   475.9   955.8   481.6  955.85   485.6  955.88
     505  968.42   514.7  971.71     534  983.82   553.4  992.74   592.1  1016.1
   601.8 1019.13   621.2 1032.06     689 1065.49   708.3 1078.29   756.7 1099.94
   776.1 1105.81   795.5 1115.04   814.8 1119.88   882.6 1147.49     931  1159.9
#Mann= 3 , 0 , 0
       0      .1       0   466.6    .045       0   481.6      .1       0
Bank Sta=466.6,481.6
XS Rating Curve= 0 ,0
Exp/Cntr=0.3,0.1

Type RM Length L Ch R = 1 ,6689.8  ,408.122,400.389,393.235
XS GIS Cut Line= 3
     1761406.852      374666.599     1761185.885      374268.857
     1760964.918      373871.115
#Sta/Elev= 30
       0 1110.35    58.1 1092.43    96.8 1075.54   116.2 1064.53   135.5 1058.22
   164.6 1041.36   193.6 1030.32   251.7 1000.51   271.1  995.21   300.1  981.58
   338.8  967.41   435.6  952.06   445.3  951.91   446.2  952.07   461.2  956.43
   474.4  962.29   542.1  980.23   561.5  989.94   580.9     995   619.6 1013.26
   629.3 1014.61   677.7 1031.16   706.7    1045   716.4 1047.74   793.8 1082.05
   832.6  1095.6   851.9 1100.59   871.3 1109.12   890.6 1114.13     910 1121.96
#Mann= 3 , 0 , 0
       0      .1       0   446.2    .045       0   461.2      .1       0
Bank Sta=446.2,461.2
XS Rating Curve= 0 ,0
Exp/Cntr=0.3,0.1

Type RM Length L Ch R = 1 ,6289.4  ,400.626,400.024,397.948
XS GIS Cut Line= 3
     1761829.093      374320.533     1761487.989      374017.892
     1761156.122      373707.066
#Sta/Elev= 30
       0 1153.57     9.7 1150.42    29.1 1137.43    58.2 1124.32   135.8 1098.12
   174.6 1076.34   203.7 1063.69   232.9 1045.41   252.3  1038.4   300.8 1012.67
   349.3  978.27     359  973.75   378.4  968.56   397.8  961.12   447.5  951.57
     456  951.29   462.5  951.77   504.4   955.6   543.1  965.01   572.1  974.55
   630.1  989.71   668.8 1002.32   688.2 1011.82   717.2 1022.01   736.6    1032
   755.9 1036.72     814 1060.68   862.3 1078.39     872 1079.64   910.7 1098.25
#Mann= 3 , 0 , 0
       0      .1       0   447.5    .045       0   462.5      .1       0
Bank Sta=447.5,462.5
XS Rating Curve= 0 ,0
Exp/Cntr=0.3,0.1

Type RM Length L Ch R = 1 ,5889.4  ,399.538,399.943,399.279
XS GIS Cut Line= 3
     1762104.553      374014.291     1761756.294      373721.605
     1761395.758      373443.268
#Sta/Elev= 30
       0 1116.04    58.1 1108.16    96.8 1099.22   125.8 1083.92   135.5 1080.93
   193.6 1048.08   212.9 1042.02     242 1026.81   290.4 1010.89   319.4  996.58
   338.8  989.01   377.5   966.7   406.5  956.09   446.5  948.39   454.9  948.31
   461.5  948.77   522.8  952.16   571.2  951.96   580.9  953.41   590.6  960.81
   629.4  983.03   648.7  988.51   668.1  999.31   716.6 1018.12   755.3 1037.87
   774.7 1043.37   813.5 1058.47   842.6 1067.06   871.6 1078.72   910.4 1090.31
#Mann= 3 , 0 , 0
       0      .1       0   446.5    .045       0   461.5      .1       0
Bank Sta=446.5,461.5
XS Rating Curve= 0 ,0
Exp/Cntr=0.3,0.1

Type RM Length L Ch R = 1 ,5489.4  ,365.804,371.462,380.488
XS GIS Cut Line= 3
     1762304.019       373756.52     1761919.533       373391.44
     1761578.548      373110.631
#Sta/Elev= 30
       0 1116.89    29.5 1106.55    49.1 1103.13     108 1079.68   147.3 1057.38
   166.9 1050.46   196.4 1028.44   255.3 1007.14   294.6  988.74     324  970.92
   333.8  969.07   363.3  954.33   422.2  946.24   461.5   951.6   521.8  945.93
   530.2   945.7   536.8  946.76   549.8  950.62   608.7   985.6   628.4  993.67
   657.8 1012.77   697.1 1029.12   726.5 1045.61   746.2 1052.52   795.2 1079.26
   844.3 1097.88     864 1102.63   922.8 1125.98   942.5 1130.68   971.9 1143.23
#Mann= 3 , 0 , 0
       0      .1       0   521.8    .045       0   536.8      .1       0
Bank Sta=521.8,536.8
XS Rating Curve= 0 ,0
Exp/Cntr=0.3,0.1

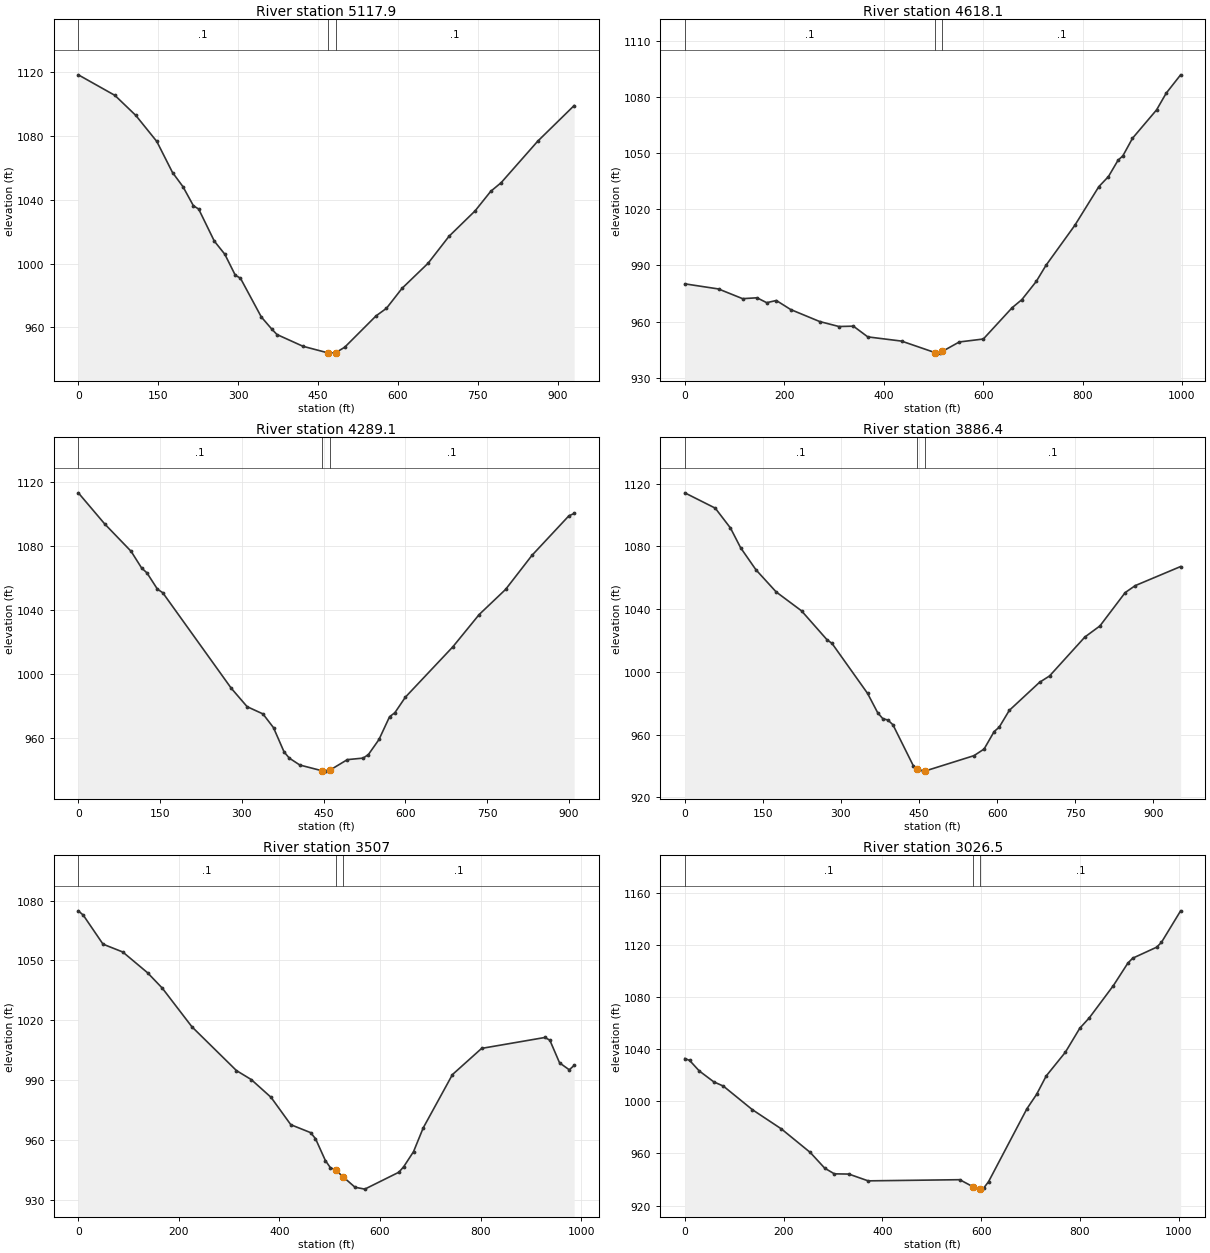
Type RM Length L Ch R = 1 ,5117.9  ,511.762,499.872,486.156
XS GIS Cut Line= 3
     1762402.803       373705.54     1762339.288      373417.872
     1762051.578      372850.442
#Sta/Elev= 30
       0 1118.36    68.7 1105.47     108 1092.88   147.3  1076.6   176.8 1057.13
   196.4 1048.26     216 1036.31   225.9 1034.22   255.3 1014.11     275  1005.9
   294.6  992.77   304.4  990.85   343.5  966.58   363.1     959   372.9  955.57
   421.8  948.19   467.9  944.13   470.8  943.91   482.9  944.16   500.1  947.62
   558.9  967.26   578.4  971.99   607.8  984.56   656.7 1000.29   695.9 1017.16
   744.8 1033.07   774.2 1045.34   793.8 1050.77   862.3 1076.73   930.8 1099.11
#Mann= 3 , 0 , 0
       0      .1       0   467.9    .045       0   482.9      .1       0
Bank Sta=467.9,482.9
XS Rating Curve= 0 ,0
Exp/Cntr=0.3,0.1

Type RM Length L Ch R = 1 ,4618.1  ,331.904,328.959,325.998
XS GIS Cut Line= 3
     1763002.621      373313.976     1762714.911      373026.265
     1762194.265      372747.863
#Sta/Elev= 30
       0  980.18    67.8  977.44   116.3  972.25   145.3  972.72   164.7   970.1
   184.1  971.27   213.1  966.42   271.3  960.02     310  957.36   339.1  957.54
   368.1  951.81   435.9  949.56   503.2  943.41   513.4  943.12   518.2  944.07
   552.1  949.09   600.5  950.67   658.5  967.44   677.9  971.72   706.9  981.46
   726.3  990.01   784.4 1011.44   832.8 1032.17   852.1 1037.55   871.5 1046.33
   881.1 1048.63   900.5 1058.05   948.9 1073.22   968.3 1082.17   997.3 1091.98
#Mann= 3 , 0 , 0
       0      .1       0   503.2    .045       0   518.2      .1       0
Bank Sta=503.2,518.2
XS Rating Curve= 0 ,0
Exp/Cntr=0.3,0.1

Type RM Length L Ch R = 1 ,4289.1  ,402.372,402.736,403.1
XS GIS Cut Line= 3
     1763140.204      372838.144     1762718.943      372666.201
     1762297.682      372494.257
#Sta/Elev= 30
       0 1113.24    48.4 1093.77    96.8 1076.65   116.2 1066.16   125.9 1063.15
   145.2 1052.93   154.9 1050.73   280.7   990.9   309.8  979.38   338.8  974.86
   358.2  966.25   377.6  951.06   387.2  947.18   406.6  942.85   446.9   939.3
     455  939.04   461.9   939.7   493.7  946.23   522.8   947.2   532.4  949.43
   551.8  958.84   571.2  973.09   580.9  975.58   600.2  985.32   687.3 1016.83
   735.7 1037.07   784.1 1052.76   832.6 1074.11   900.3 1098.85     910 1100.31
#Mann= 3 , 0 , 0
       0      .1       0   446.9    .045       0   461.9      .1       0
Bank Sta=446.9,461.9
XS Rating Curve= 0 ,0
Exp/Cntr=0.3,0.1

Type RM Length L Ch R = 1 ,3886.4  ,369.487,379.356,390.178
XS GIS Cut Line= 3
     1763312.642      372483.574     1762837.234      372280.474
     1762403.214      372242.441
#Sta/Elev= 30
       0 1114.22    58.5 1104.46    87.8 1091.76   107.3 1079.19   136.6  1065.2
   175.6 1051.02   224.3 1038.98   273.1  1020.6   282.9  1018.2   351.2  986.34
   370.7  973.97   380.4  970.26   390.2  969.34   399.9  966.35   438.9  940.33
     447  938.19   458.4  936.78     462  936.88   555.7  946.65   575.1  950.88
   594.4  962.01   604.1   964.8   623.5  975.52   681.6  993.41   700.9  997.47
   768.7 1022.28   797.7 1029.37   846.2 1050.62   865.5 1055.06   952.7 1067.23
#Mann= 3 , 0 , 0
       0      .1       0     447    .045       0     462      .1       0
Bank Sta=447,462
XS Rating Curve= 0 ,0
Exp/Cntr=0.3,0.1

Type RM Length L Ch R = 1 ,3507    ,481.031,480.57,479.702
XS GIS Cut Line= 3
     1763414.628      372176.645     1762908.825      371935.943
     1762483.754      371965.026
#Sta/Elev= 30
       0  1074.9     9.8 1072.74    49.1 1058.18    88.4 1054.25   137.6 1043.86
   167.1 1036.09     226 1016.71   314.5  994.77     344  990.25   383.3  981.35
   422.6  967.62   461.9  963.65   471.7  960.63   491.4  949.63   501.2  946.11
   512.1  944.84   527.1  941.36   550.3  936.25   569.8   935.3   637.6  943.79
   647.3  946.59   666.7  954.09     686  966.03   744.1  992.76   802.2  1005.9
   928.1 1011.37   937.8 1010.02   957.2  998.64   976.5  995.15   986.2  997.38
#Mann= 3 , 0 , 0
       0      .1       0   512.1    .045       0   527.1      .1       0
Bank Sta=512.1,527.1
XS Rating Curve= 0 ,0
Exp/Cntr=0.3,0.1

Type RM Length L Ch R = 1 ,3026.5  ,578.569,579.35,579.584
XS GIS Cut Line= 3
     1763602.361      371880.012     1763137.021      371611.546
     1762834.997      371255.829
#Sta/Elev= 30
       0 1032.86     9.8 1031.37    29.3  1023.3    58.6 1014.96    78.1 1011.66
   136.7   993.6   195.4  978.84     254  960.73   283.3  948.67   302.8  944.31
   332.1  944.13   371.2  938.92   556.7  939.81   583.2  934.45   595.6  932.57
   598.2   932.8   605.3  933.44     615  938.28   692.8  994.36   712.2 1005.27
   731.7 1019.43   770.5 1037.66   799.7 1056.08   819.2 1064.18   867.8 1088.88
   896.9    1106   906.7 1109.85   955.3 1118.31     965 1121.99  1003.9 1146.24
#Mann= 3 , 0 , 0
       0      .1       0   583.2    .045       0   598.2      .1       0
Bank Sta=583.2,598.2
XS Rating Curve= 0 ,0
Exp/Cntr=0.3,0.1

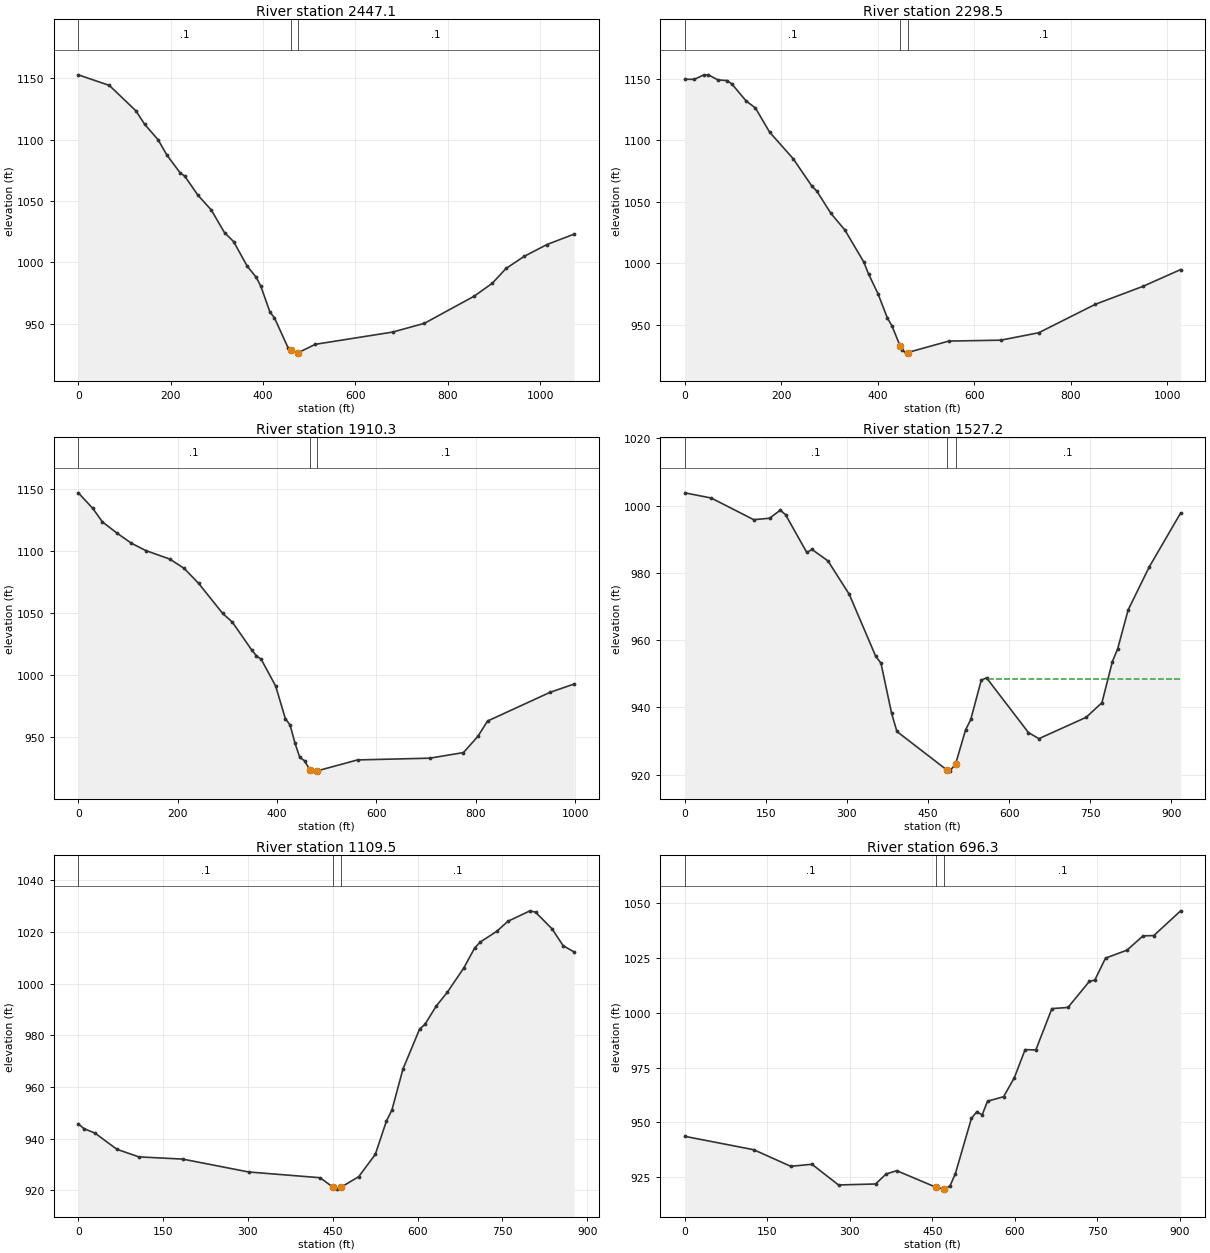
Type RM Length L Ch R = 1 ,2447.1  ,150.493,148.594,146.695
XS GIS Cut Line= 3
     1763977.641      371907.391     1763753.866      371683.616
     1763261.721      371108.567
#Sta/Elev= 30
       0 1152.83    67.1  1144.2   124.7 1123.46   143.8 1112.41   172.6 1099.94
   191.8 1087.36   220.6 1072.84   230.2 1070.34   258.9  1054.7   287.7 1042.72
   316.5 1024.13   336.1 1016.91   365.6  996.83   385.3  987.69   395.1  980.46
   414.8  959.43   424.6  954.68   454.1  930.27   460.1  928.17   473.7  925.93
   475.1  926.13   513.1  933.13   680.2  943.08     749  950.21   857.1  972.39
   896.4  982.97   925.9  994.96   965.2 1004.82  1014.4 1014.45  1073.4 1022.97
#Mann= 3 , 0 , 0
       0      .1       0   460.1    .045       0   475.1      .1       0
Bank Sta=460.1,475.1
XS Rating Curve= 0 ,0
Exp/Cntr=0.3,0.1

Type RM Length L Ch R = 1 ,2298.5  ,399.329,388.193,377.057
XS GIS Cut Line= 3
       1764095.9      371767.956     1763776.687       371480.28
     1763350.714      371060.169
#Sta/Elev= 30
       0 1149.89    19.5 1149.71    39.1 1153.34    48.8 1153.44    68.4 1149.34
    87.9 1148.74    97.7 1145.97     127 1132.22   146.5 1126.41   175.8 1106.78
   224.6 1085.16   263.7 1062.64   273.5 1058.86   302.8 1040.64   332.1  1026.9
   371.1 1000.95   380.9  991.27   400.4  975.26   419.9  955.48   429.7  948.72
   446.8  932.18   449.3  929.65   459.1  926.72   461.8  927.19   547.4  936.54
   655.3  937.28   733.8  943.33   851.5  966.57   949.5  981.06    1028   994.8
#Mann= 3 , 0 , 0
       0      .1       0   446.8    .045       0   461.8      .1       0
Bank Sta=446.8,461.8
XS Rating Curve= 0 ,0
Exp/Cntr=0.3,0.1

Type RM Length L Ch R = 1 ,1910.3  ,395.113,383.16,371.207
XS GIS Cut Line= 3
     1764375.067      371131.217     1763939.065      371121.959
     1763399.281      370965.156
#Sta/Elev= 30
       0 1146.78    29.1 1134.25    48.5 1123.37    77.5 1114.42   106.6 1106.25
   135.7  1100.3   184.1 1093.41   213.2 1085.89   242.3 1073.78   290.7  1049.6
   310.1 1042.64   348.9 1020.27   358.6  1015.5   368.3 1012.57   397.3  991.12
   416.7  964.97   426.4  959.69   436.1  945.18   445.8  933.73   455.5  930.94
   465.9  923.73   474.9  922.61   480.9  922.82   562.1  931.64   707.5  933.04
   775.3  937.56   804.4  950.62   823.8  962.96   949.7  986.09   998.2  992.77
#Mann= 3 , 0 , 0
       0      .1       0   465.9    .045       0   480.9      .1       0
Bank Sta=465.9,480.9
XS Rating Curve= 0 ,0
Exp/Cntr=0.3,0.1

Type RM Length L Ch R = 1 ,1527.2  ,406.804,417.621,428.438
XS GIS Cut Line= 3
      1764258.23      370583.317     1763826.727      370745.645
     1763384.433      370857.356
#Sta/Elev= 30
       0 1003.79      49 1002.24   127.5  995.81   156.9  996.24   176.6  998.63
   186.4  997.29   225.6  986.08   235.4  986.95   264.8  983.56   304.1  973.66
   353.1  955.24   362.9  953.15   382.6  938.23   392.4  932.85   485.9  921.28
   490.1  921.07   500.9  923.19   519.3  933.28     529  936.43   548.4  948.08
   558.1  948.81   635.7  932.53   655.1  930.72   742.5  937.07   771.6  941.41
     791  953.64   800.7  957.39   820.1  968.98     859  981.72   917.2  997.79
#Mann= 3 , 0 , 0
       0      .1       0   485.9    .045       0   500.9      .1       0
#XS Ineff= 2 , 0
                          560.18          948.59
Permanent Ineff=
       F       F
Bank Sta=485.9,500.9
XS Rating Curve= 0 ,0
Exp/Cntr=0.3,0.1

Type RM Length L Ch R = 1 ,1109.5  ,400.593,413.269,426.522
XS GIS Cut Line= 3
     1764184.037      370441.483     1763765.474      370354.184
     1763327.934       370252.27
#Sta/Elev= 30
       0  945.78     9.7   943.9    29.2   942.2      68  935.93   106.9  932.97
   184.6  932.11   301.2  927.13   427.6  924.91     450  921.29   456.9   920.5
     465   921.3   495.9  925.34   525.2  933.96   544.8  946.82   554.5  951.08
   574.1  966.95   603.4  982.33   613.1  984.26   632.7  991.22   652.2  996.53
   681.5 1005.96     701 1013.79   710.8 1016.04   740.1 1020.21   759.6 1024.05
   798.7  1028.1   808.5 1027.58   837.8 1021.11   857.3 1014.62   876.8 1012.19
#Mann= 3 , 0 , 0
       0      .1       0     450    .045       0     465      .1       0
Bank Sta=450,465
XS Rating Curve= 0 ,0
Exp/Cntr=0.3,0.1

Type RM Length L Ch R = 1 ,696.3   ,388.961,398.318,407.097
XS GIS Cut Line= 3
     1764273.526      370322.911     1763947.937      370008.005
     1763640.762      369681.046
#Sta/Elev= 30
       0  943.68   125.3  937.57   192.7     930   231.3  930.93   279.5  921.48
   346.9  921.93   366.2  926.52   385.5  927.99   456.6  920.45   471.6  919.61
   472.5  919.58   482.2  921.04     492  926.64   521.2  951.89     531  954.93
   540.7  953.47   550.5  959.72   579.7  961.77   599.2  970.43   618.8  983.27
   638.3  983.11   667.5 1001.98   696.8 1002.53   735.8 1014.47   745.5 1014.98
     765 1025.04   804.1 1028.68   833.3 1035.21   852.8 1035.33   901.6 1046.63
#Mann= 3 , 0 , 0
       0      .1       0   456.6    .045       0   471.6      .1       0
Bank Sta=456.6,471.6
XS Rating Curve= 0 ,0
Exp/Cntr=0.3,0.1

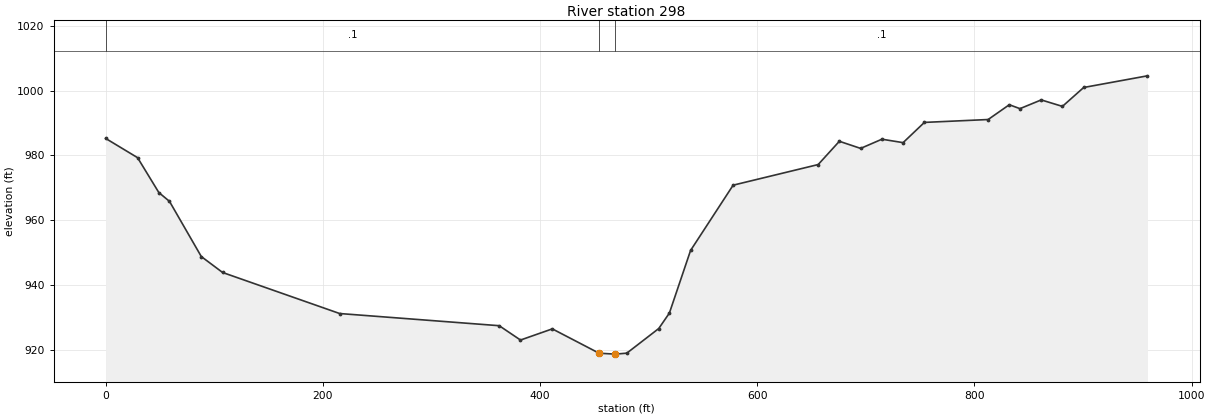
Type RM Length L Ch R = 1 ,298     ,308.947,297.951,286.955
XS GIS Cut Line= 3
     1764471.371      370275.354      1764257.36      369717.592
     1763945.673      369533.777
#Sta/Elev= 30
       0  985.27    29.4  979.32      49  968.54    58.8  965.82    88.1  948.77
   107.7  943.85   215.5  931.17   362.4  927.41     382  922.98   411.3  926.43
   454.4  918.91   469.4  918.63   479.9  918.93   509.3  926.54   519.1  931.31
   538.6  950.65   577.8  970.82   656.1  977.19   675.6  984.38   695.2  982.18
   714.8  985.02   734.3  983.96   753.9  990.21   812.6   991.1   832.1  995.67
   841.9  994.46   861.5  997.16     881  995.16   900.6    1001   959.3  1004.6
#Mann= 3 , 0 , 0
       0      .1       0   454.4    .045       0   469.4      .1       0
Bank Sta=454.4,469.4
XS Rating Curve= 0 ,0
Exp/Cntr=0.3,0.1

Chan Stop Cuts=-1
Use User Specified Reach Order=0